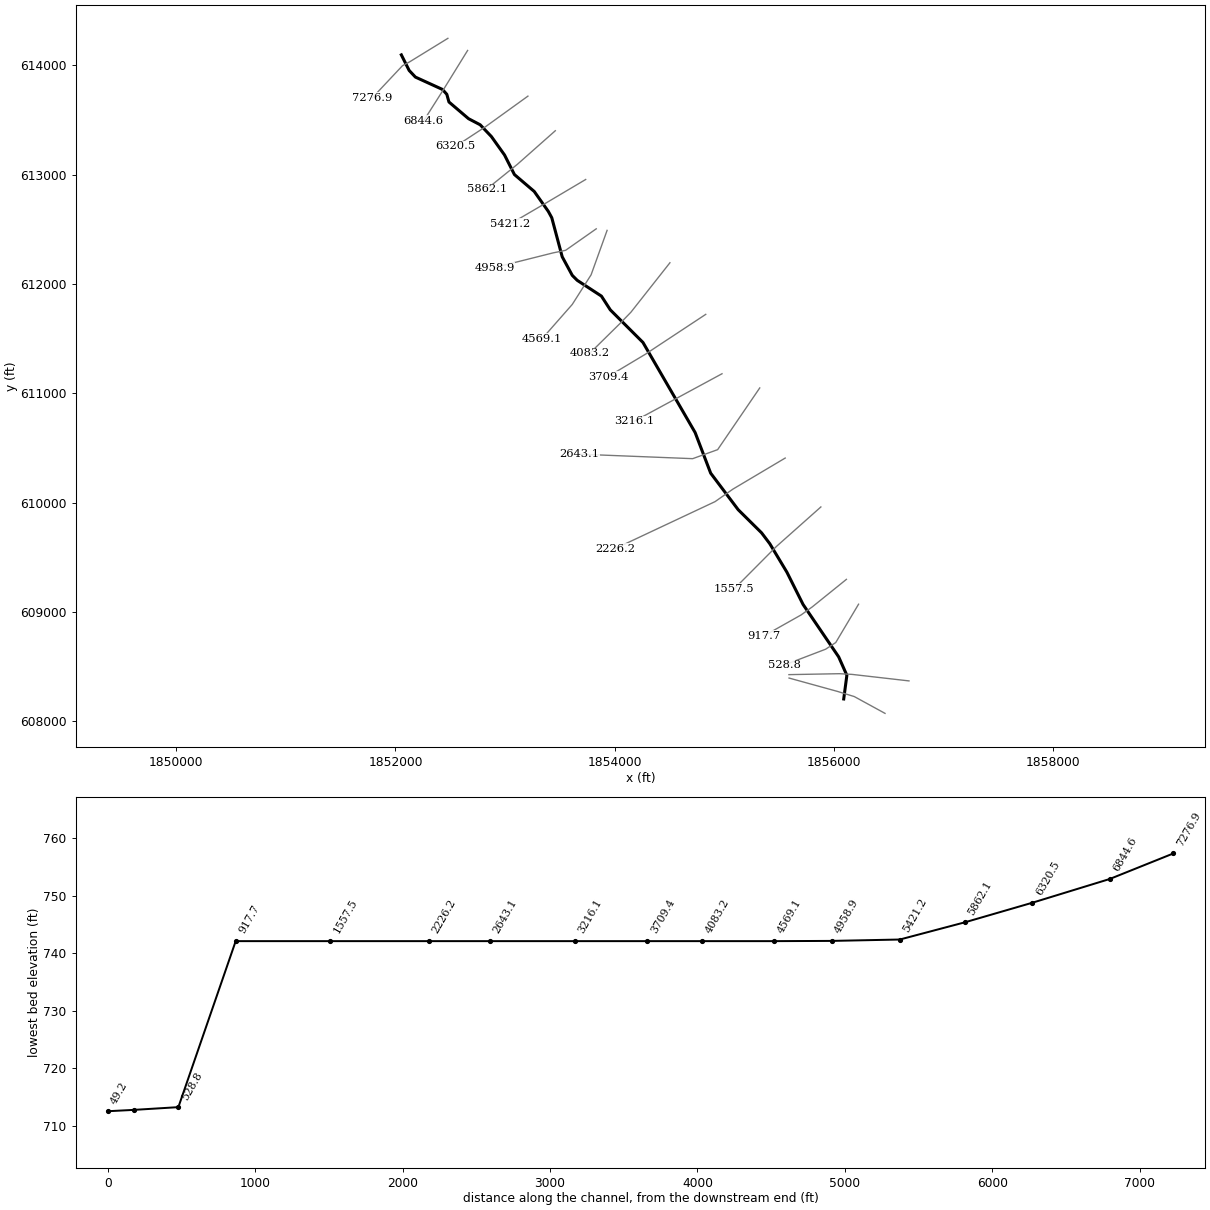
--- SilcottFrk.prj (project) ---

Proj Title=SilcottFrk
Current Plan=p01
Default Exp/Contr=0,0
English Units
Geom File=g01
Flow File=f01
Plan File=p01
BEGIN DESCRIPTION:
AMEC Environment & Infrastructure, 2013
Projection: NAD 1983 State Plane West Virginia South FIPS 4702 (US Feet)
Vertical Datum: NAVD 1988
END DESCRIPTION:
DSS Export Rating Curves= 0
DSS Export Rating Curve Sorted= 0
DSS Export Volume Flow Curves= 0
DXF OffsetX= 0
DXF OffsetY= 0
DXF ScaleX= 0
DXF ScaleY= 0

--- SilcottFrk.p01 (plan) ---

Plan Title=Floodplain
Program Version=4.00
Geom File=g01
Flow File=f01
K Sum by GR=0
Std Step Tol=0.01
Critical Tol=0.01
Num of Std Step Trials=20
Max Error Tol=0.3
Flow Tol Ratio=0.001
Split Flow NTrial=30
Split Flow Tol=0.02
Split Flow Ratio=0.02
Log Output Level=0
Friction Slope Method=1
Unsteady Friction Slope Method=2
Unsteady Bridges Friction Slope Method=1
Global Log Level=0
CheckData=False
Run HTab=0
Run UNet=0
Run PostProcess=0
UNET Theta=0
UNET Theta Warmup=0
UNET ZTol=0
UNET ZSATol=0
UNET MxIter=0
UNET MaxInSteps=0
UNET DtIC=0
UNET DtMin=0
UNET MaxCRTS=0
UNET WFStab=0
UNET SFStab=0
UNET WFX=0
UNET SFX=0
UNET DSS MLevel=0
UNET DZMax Abort=0
UNET Convert EG Bridges=0
UNET Use Existing IB Tables=0
UNET Froude Limit=0
UNET Froude Power=0
Write IC File=0
Echo Input=False
Echo Output=False
Write Detailed=0

--- SilcottFrk.f01 (steady flow) ---

Flow Title=NFF Regression Equation
Program Version=4.10
Number of Profiles= 1
Profile Names=P100yr
River Rch & RM=SilcottFrk,Main            ,7276.9
827.7684
River Rch & RM=SilcottFrk,Main            ,6844.6
921.3435
River Rch & RM=SilcottFrk,Main            ,4569.1
1007.708
River Rch & RM=SilcottFrk,Main            ,2643.1
1096.046
River Rch & RM=SilcottFrk,Main            ,2226.2
1212.186
River Rch & RM=SilcottFrk,Main            ,917.7
 1232.72
River Rch & RM=SilcottFrk,Main            ,230.2
1235.276
Boundary for River Rch & Prof#=SilcottFrk,Main            , 1
Up Type= 0
Dn Type= 3
Dn Slope=0.00342
DSS Import GetInterval= 0
DSS Import GetPeak= 0
DSS Import FillOption= 0

--- SilcottFrk.g01 (geometry) ---

Geom Title=USGS 3m DEM
Program Version=4.10

River Reach=SilcottFrk      ,Main
Reach XY= 30
     1852054.092      614094.394     1852125.305      613951.987
     1852182.619      613891.204     1852429.239       613778.33
     1852468.942      613733.778     1852488.292      613663.709
     1852667.182      613510.887     1852773.124      613455.317
     1852875.595      613347.646     1852995.437       613179.19
     1853085.755      613000.313     1853266.381      612845.754
     1853394.906      612663.405      1853426.51      612605.261
     1853521.707      612248.336     1853613.761      612078.142
     1853658.917       612032.99     1853879.487      611888.853
     1853960.356      611763.305     1854258.399      611465.262
     1854734.531      610641.353     1854876.239      610270.103
     1855127.061      609936.265     1855340.687      609724.395
      1855415.37      609625.406     1855571.788      609364.481
     1855719.168      609069.721     1856044.108      608590.353
     1856118.795      608421.896     1856090.186      608205.667

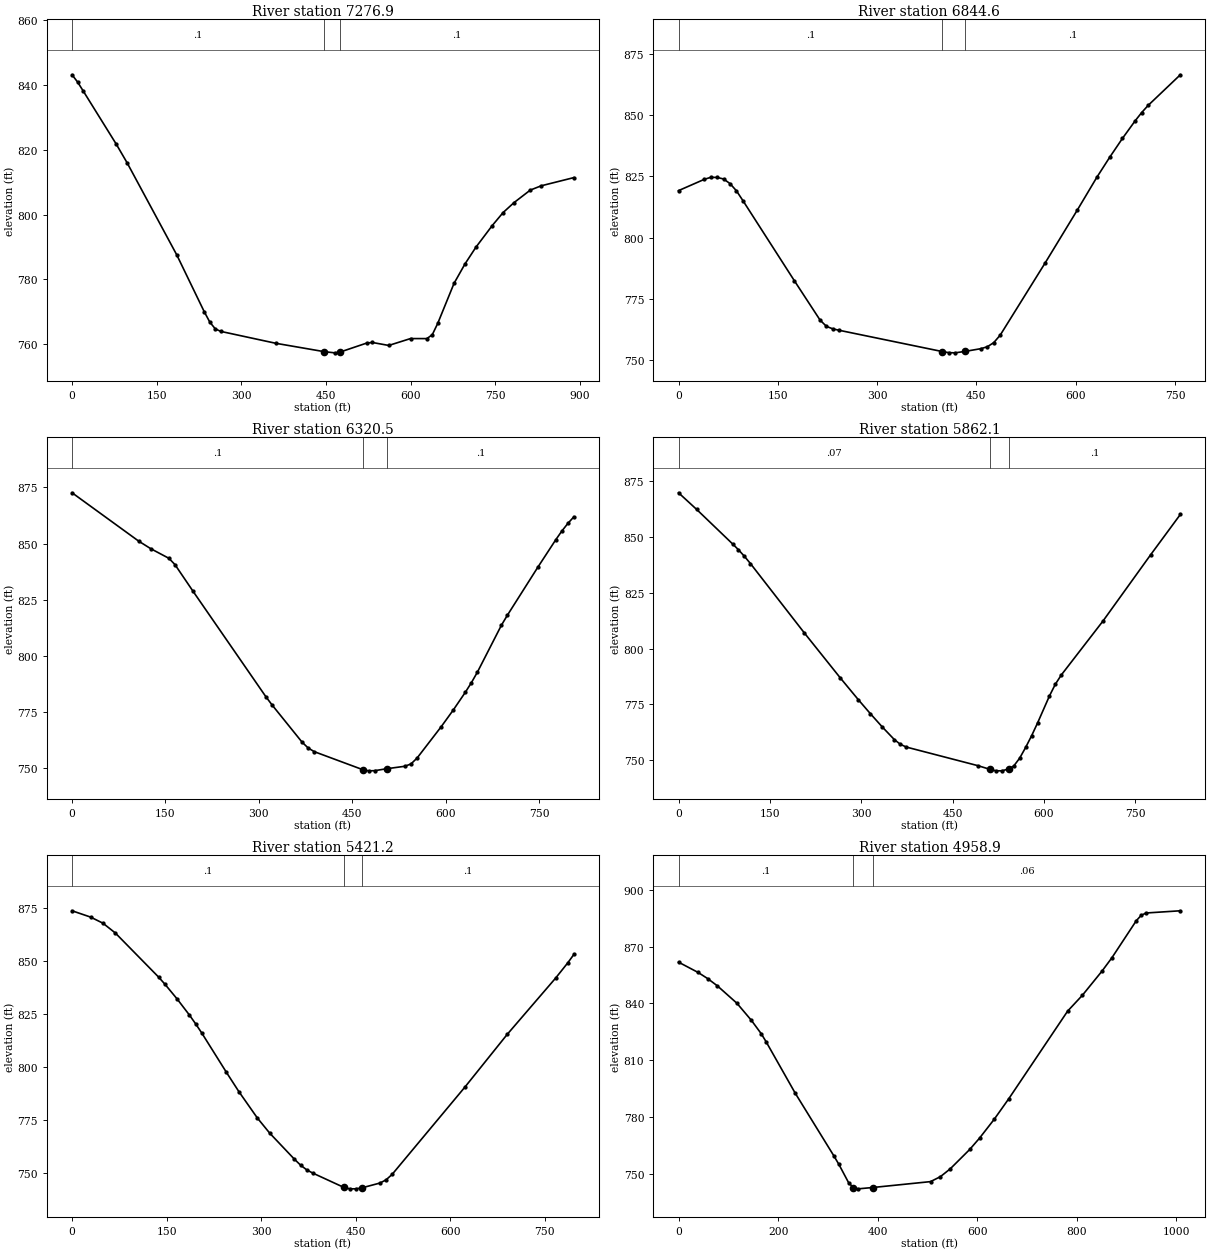
Type RM Length L Ch R = 1 ,7276.9  ,420.3,432.3,444
XS GIS Cut Line= 4
     1852478.635      614245.649     1852129.512      614030.627
     1852064.408       613995.47     1851787.064      613699.897
#Sta/Elev= 30
       0   843.1     9.8  840.86    19.5  838.17    78.1  821.77    97.6  815.94
   185.5  787.57   234.3  770.01   244.1  766.83   253.8  764.74   263.6  763.96
   361.2  760.29     447  757.71   465.5  757.35   474.8  757.58   522.6  760.39
   532.3  760.54   561.2  759.63   599.8  761.75   628.8  761.74   638.4  762.94
   648.1  766.45     677   778.8   696.3  784.75   715.6   789.9   744.6  796.59
   763.9  800.61   783.2  803.67   812.1  807.54   831.4  808.86   889.3  811.39
#Mann= 3 , 0 , 0
       0      .1       0     447    .045       0   474.8      .1       0
Bank Sta=447,474.8
XS Rating Curve= 0 ,0
Exp/Cntr=0.3,0.1

Type RM Length L Ch R = 1 ,6844.6  ,533.5,524,514.1
XS GIS Cut Line= 3
     1852658.592      614134.793     1852434.344      613770.672
      1852257.55      613491.564
#Sta/Elev= 30
       0   819.2    38.9  823.81    48.6  824.63    58.3  824.59      68  823.96
    77.8  822.07    87.5  819.11    97.2  815.14   174.9   782.4   213.8  766.29
   223.5   763.7   233.3  762.68     243   762.1   398.5  753.42   408.2  752.98
   417.7   752.9   432.7  753.48   456.8  754.61   466.5  755.39   476.2  757.08
   485.9  760.13     554  789.73   602.6  811.35   631.7  824.57   651.1  832.75
   670.6  840.56     690  847.82   699.7  851.13   709.4  854.04     758  866.55
#Mann= 3 , 0 , 0
       0      .1       0   398.5    .045       0   432.7      .1       0
Bank Sta=398.5,432.7
XS Rating Curve= 0 ,0
Exp/Cntr=0.3,0.1

Type RM Length L Ch R = 1 ,6320.5  ,455.9,458.4,461.2
XS GIS Cut Line= 3
     1853208.939      613717.259     1852822.768      613438.164
      1852547.48      613257.189
#Sta/Elev= 30
       0  872.64     107   851.1   126.4  847.73   155.6  843.44   165.3  840.63
   194.5  828.68   311.2  781.82   320.9  778.24   369.5  761.52   379.2  758.96
     389  757.32   466.7  749.32   476.5  748.78   486.2  748.86   505.5  749.73
   534.6  750.82   544.3  751.86     554  754.44   592.7  768.39   612.1  775.82
   631.5  783.73   641.2  787.99   650.9   792.7   689.6  813.67   699.3  818.17
   747.8  839.38   776.8   851.7   786.5  855.55   796.2  858.97   805.9  861.93
#Mann= 3 , 0 , 0
       0      .1       0   466.7    .045       0   505.5      .1       0
Bank Sta=466.7,505.5
XS Rating Curve= 0 ,0
Exp/Cntr=0.3,0.1

Type RM Length L Ch R = 1 ,5862.1  ,444.5,440.9,437
XS GIS Cut Line= 3
     1853458.789      613400.865     1853112.842      613094.034
     1852832.203      612866.564
#Sta/Elev= 30
       0  869.55    29.5  862.18    88.6  846.75    98.4   844.1   108.2  841.16
   118.1  837.92   206.6  806.93   265.6  786.85   295.2  777.12   314.8  770.93
   334.5  764.95   354.2  759.34     364  757.24   373.9  755.99   491.7  747.66
   511.2  746.04     521  745.39   530.8  745.37   541.9  746.23   550.3  747.55
     560  751.04   569.8  755.83   579.6  761.05   589.3  766.71   608.9  778.84
   618.6  784.08   628.4  788.21   696.7  812.26   774.8   841.8   823.7  859.86
#Mann= 3 , 0 , 0
       0     .07       0   511.2    .045       0   541.9      .1       0
Bank Sta=511.2,541.9
XS Rating Curve= 0 ,0
Exp/Cntr=0.3,0.1

Type RM Length L Ch R = 1 ,5421.2  ,469.6,462.4,454.9
XS GIS Cut Line= 3
     1853735.848      612955.106     1853381.909      612744.871
     1853050.085      612550.592
#Sta/Elev= 30
       0  873.57    29.4  870.59      49  867.71    68.6   863.1   137.2  842.32
     147  839.05   166.6     832   186.2  824.38     196  820.26   205.8   815.9
     245  797.31   264.6  788.28     294   775.8   313.6  768.66   352.9  756.33
   362.7  753.52   372.5   751.3   382.3  749.76   430.9  743.11   440.5   742.4
   450.1  742.38   459.7  742.84   488.6  745.12   498.2  746.62   507.8  749.18
   623.2  790.34   690.4  815.24   767.4  841.86   786.6  849.03   796.2  852.96
#Mann= 3 , 0 , 0
       0      .1       0   430.9    .045       0   459.7      .1       0
Bank Sta=430.9,459.7
XS Rating Curve= 0 ,0
Exp/Cntr=0.3,0.1

Type RM Length L Ch R = 1 ,4958.9  ,371.6,389.8,407.8
XS GIS Cut Line= 4
     1853832.203      612504.076     1853552.689      612307.536
     1853439.621      612284.302     1852905.119      612149.909
#Sta/Elev= 30
       0  861.77      39  856.38    58.6  853.09    78.1  849.25   117.2  840.12
   146.4  831.06     166  824.07   175.7  819.89   234.3   792.7   312.4  759.42
   322.2  755.05   341.7  745.41   351.3  742.74   360.9  742.14   389.8  742.83
   506.3  745.95     526  748.53   545.7  752.63   585.1  762.92   604.8  768.89
   634.3  778.84   663.8  789.77   781.9  835.95   811.4  844.26   850.8     857
   870.5  863.97   919.7  883.59   929.5  886.44   939.4  887.71  1008.3  888.88
#Mann= 3 , 0 , 0
       0      .1       0   351.3    .045       0   389.8     .06       0
Bank Sta=351.3,389.8
XS Rating Curve= 0 ,0
Exp/Cntr=0.3,0.1

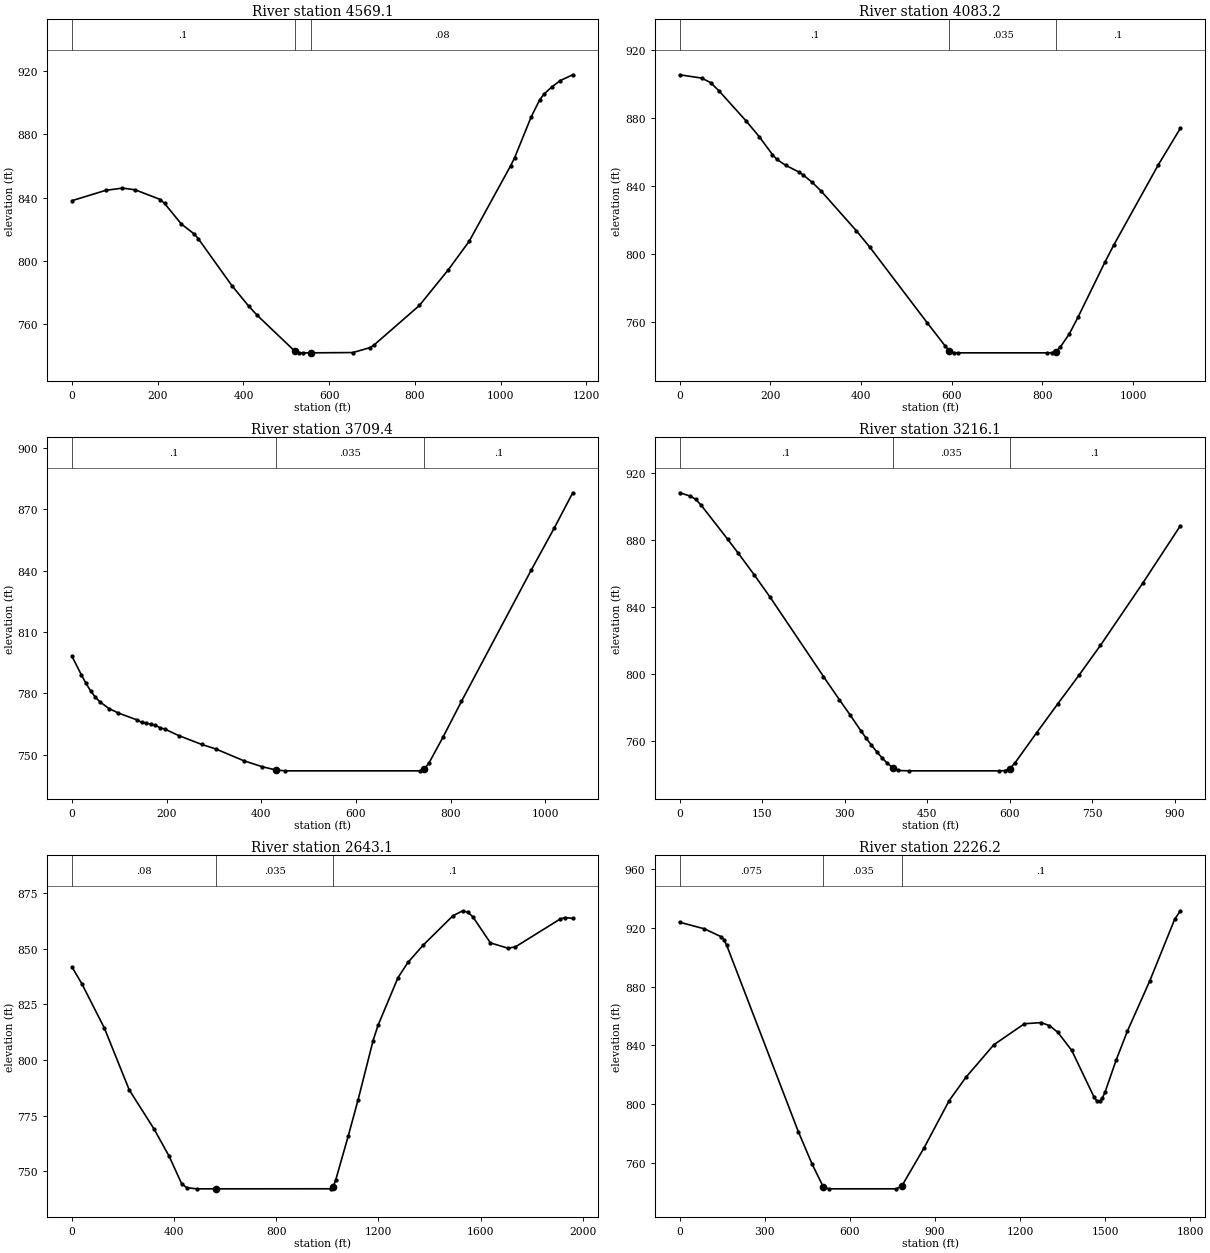
Type RM Length L Ch R = 1 ,4569.1  ,490.4,485.9,481.4
XS GIS Cut Line= 4
     1853931.161      612489.828     1853785.328      612083.578
     1853613.453      611812.745     1853339.147      611500.245
#Sta/Elev= 30
       0  838.18    78.5  844.68   117.7  846.12   147.2  845.04     206  838.91
   215.8  836.46   255.1  823.45   284.5  817.26   294.3  814.28   372.8  784.61
     412  771.66   431.6  765.91   519.1  743.33   528.6  742.13   538.6   742.1
     558   742.1   655.2  742.28   694.1  745.31   703.8  746.86   810.4     772
   878.1  794.62   926.5  812.51  1023.2  860.17  1032.8  865.43  1071.5  891.23
  1090.8  901.66  1100.5  905.35  1119.9   910.1  1139.2  914.02  1168.2  917.66
#Mann= 3 , 0 , 0
       0      .1       0   519.1    .045       0     558     .08       0
Bank Sta=519.1,558
XS Rating Curve= 0 ,0
Exp/Cntr=0.3,0.1

Type RM Length L Ch R = 1 ,4083.2  ,378.6,373.8,369
XS GIS Cut Line= 4
     1854504.512      612193.821      1854148.95      611742.092
     1854046.612      611636.095     1853774.776      611367.918
#Sta/Elev= 30
       0  905.18    48.7  903.23    68.2   900.6    87.7  895.49   146.2  878.19
   175.4  868.91   204.6  858.41   214.4  855.53   233.8   852.1   263.1  848.12
   272.8  846.38   292.3  842.07   311.8  837.06   389.8  813.64     419  804.18
   545.6  759.82   584.7  746.39   594.5  743.38   604.3  742.16   614.2   742.1
   810.3   742.1   820.1  742.18   829.9  742.87   839.7  745.61   859.3  753.26
   878.9  763.27   937.6  795.22   957.2  805.31  1055.1  852.22  1104.1  873.82
#Mann= 3 , 0 , 0
       0      .1       0   594.5    .035       0   829.9      .1       0
Bank Sta=594.5,829.9
XS Rating Curve= 0 ,0
Exp/Cntr=0.3,0.1

Type RM Length L Ch R = 1 ,3709.4  ,495.5,493.3,491.2
XS GIS Cut Line= 4
     1854831.335      611722.033     1854373.827      611419.653
      1854284.46       611359.62     1853939.954      611152.961
#Sta/Elev= 30
       0  798.12    19.6  789.12    29.4  784.93    39.2  781.25      49  778.22
    58.8   775.9    78.3  772.55    97.9  770.38   137.1  767.04   146.9  765.82
   156.7  765.56   166.5  764.78   176.3  764.41   186.1  763.16   195.9  762.55
   225.2  759.37   274.2  754.99   303.6  752.82   362.3   747.1   401.5  744.13
   430.9   742.5   450.5   742.1   734.4   742.1   744.2  742.89     754   745.9
   783.4  758.44   822.6  776.04   969.6  840.12  1018.6  860.83  1057.8  878.14
#Mann= 3 , 0 , 0
       0      .1       0   430.9    .035       0   744.2      .1       0
Bank Sta=430.9,744.2
XS Rating Curve= 0 ,0
Exp/Cntr=0.3,0.1

Type RM Length L Ch R = 1 ,3216.1  ,576.3,573,569.6
XS GIS Cut Line= 3
     1854979.738      611179.048     1854579.735        610962.2
     1854179.733      610745.351
#Sta/Elev= 30
       0  908.12    19.4  906.14      29  904.28    38.7  900.88    87.1  880.45
   106.5  872.06   135.5  859.14   164.6  845.69   261.4  798.42   290.4  784.52
   309.8  775.48   329.2  766.11   338.8  761.69   348.5  757.45   358.2  753.48
   367.9  749.81   377.6  746.58   387.2  743.96   396.9  742.31   416.3   742.1
   580.8   742.1   590.5  742.22   600.2  743.35   609.9  747.06   648.6  764.76
   687.3  782.14   726.1  799.35   764.8  817.03   842.2  854.45     910  888.44
#Mann= 3 , 0 , 0
       0      .1       0   387.2    .035       0   600.2      .1       0
Bank Sta=387.2,600.2
XS Rating Curve= 0 ,0
Exp/Cntr=0.3,0.1

Type RM Length L Ch R = 1 ,2643.1  ,410.9,416.9,422.9
XS GIS Cut Line= 4
     1855323.956       611049.29     1854939.842      610485.054
     1854711.977      610402.588     1853676.821      610443.821
#Sta/Elev= 30
       0  841.69      39  834.08   126.8  814.26   224.3  786.48   321.8  768.86
   380.3  756.75     429  744.47   448.6  742.65   487.6   742.1   565.6   742.1
  1012.9  742.12  1022.6  743.06  1032.4  745.97  1081.3  765.65  1120.4  782.12
    1179  808.68  1198.6   815.6  1276.7  836.97  1315.8   843.8  1374.5  851.45
  1491.8  864.74  1530.8  866.96  1550.4  866.28  1569.9  864.23  1638.4  852.55
  1706.8  850.16  1736.1  850.74    1912  863.28  1931.6  863.93  1960.9  863.52
#Mann= 3 , 0 , 0
       0     .08       0   565.6    .035       0  1022.6      .1       0
Bank Sta=565.6,1022.6
XS Rating Curve= 0 ,0
Exp/Cntr=0.3,0.1

Type RM Length L Ch R = 1 ,2226.2  ,664.7,668.7,672.7
XS GIS Cut Line= 4
     1855556.161      610408.231     1855079.598      610124.377
     1854916.404      610009.793     1854001.473      609578.729
#Sta/Elev= 30
       0  923.85    87.6  919.32     146     914   155.7  912.06   165.4  908.39
   418.4   781.1   467.1  758.94     506  743.62   525.5   742.1   763.9  742.11
   783.6   744.1   862.1  770.15   950.5  802.31  1009.4  818.15  1107.6  840.28
  1215.6  854.65  1274.5  855.42    1304  853.34  1333.4  848.83  1382.5  836.43
  1461.1  804.65  1470.9  802.01  1480.7  801.68  1490.6  804.01  1500.4  808.31
  1539.6  830.17  1578.9  849.72  1657.5  883.82  1745.8  926.02  1765.5  931.65
#Mann= 3 , 0 , 0
       0    .075       0     506    .035       0   783.6      .1       0
Bank Sta=506,783.6
XS Rating Curve= 0 ,0
Exp/Cntr=0.3,0.1

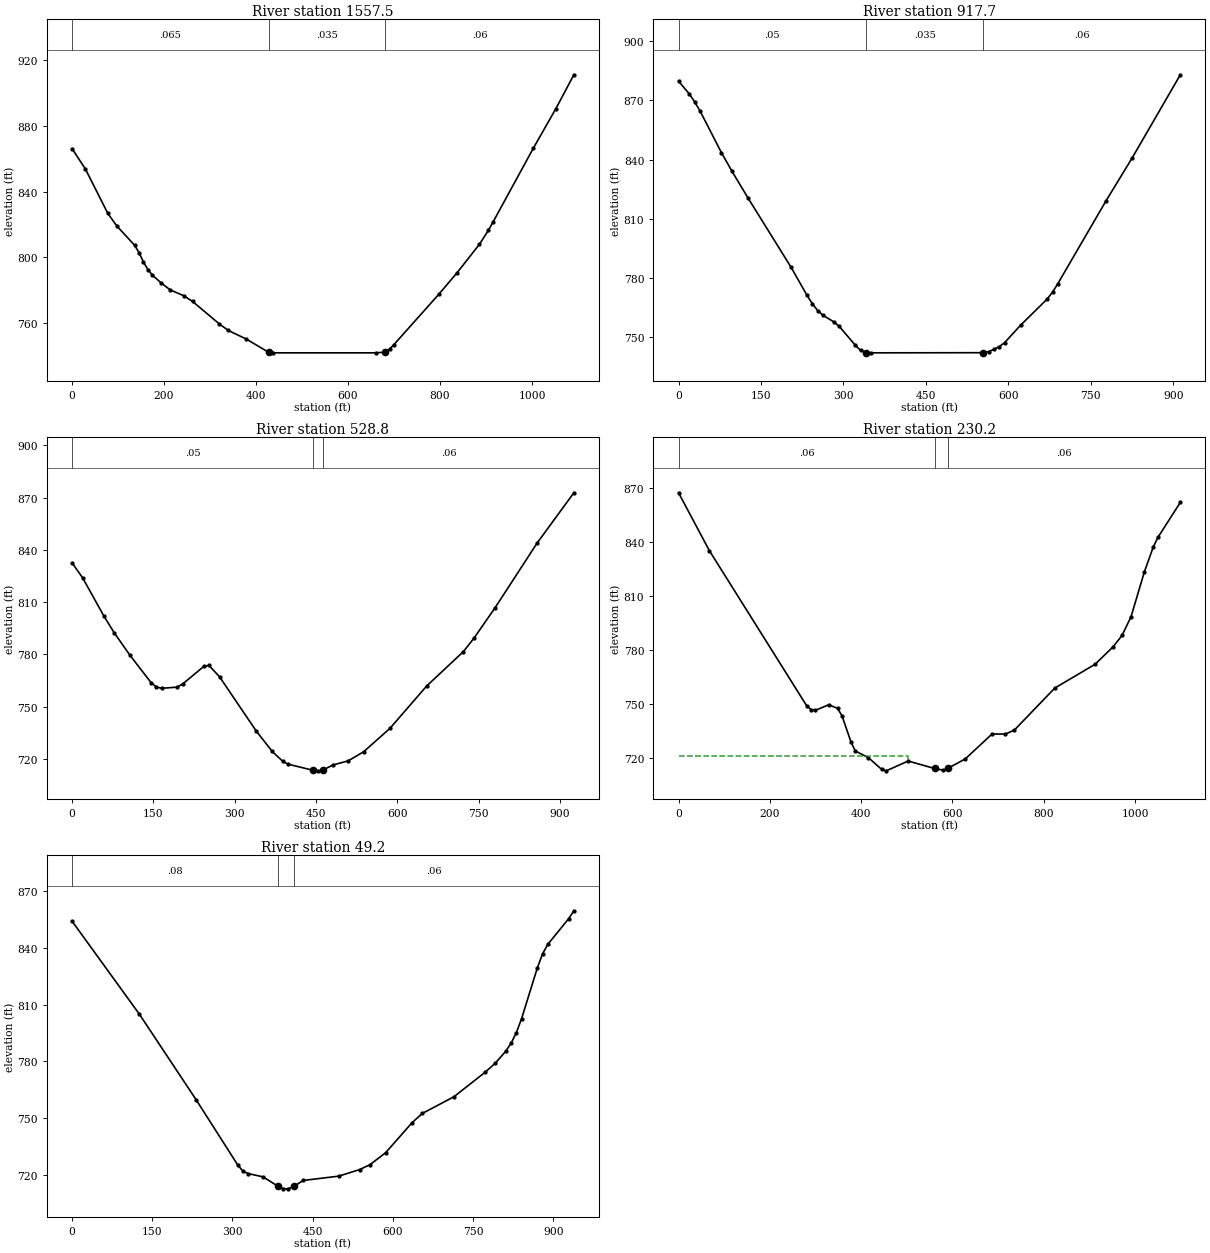
Type RM Length L Ch R = 1 ,1557.5  ,643.5,639.8,636.1
XS GIS Cut Line= 3
     1855881.682      609961.182     1855475.759      609599.578
     1855090.015      609211.182
#Sta/Elev= 30
       0  866.07    29.1  853.62    77.7  826.74    97.1  819.16   135.9  807.42
   145.6  802.92   155.3  797.15     165   792.6   174.7  789.29   194.2  784.39
   213.6  780.28   242.7  776.78   262.1  773.27   320.4  759.59   339.8  755.67
   378.6   750.5   427.1  742.46   436.8   742.1   660.9   742.1   680.5  742.54
   690.2  744.34     700  747.16   797.8  777.78   836.9  790.65   885.8  808.02
   905.3  816.55   915.1  821.41    1003  866.37  1051.9  890.33    1091  910.88
#Mann= 3 , 0 , 0
       0    .065       0   427.1    .035       0   680.5     .06       0
Bank Sta=427.1,680.5
XS Rating Curve= 0 ,0
Exp/Cntr=0.3,0.1

Type RM Length L Ch R = 1 ,917.7   ,389.8,388.8,387.9
XS GIS Cut Line= 4
     1856114.646       609299.09     1855803.991      609047.988
     1855701.994      608974.203     1855364.506      608783.625
#Sta/Elev= 30
       0  879.74    19.5   873.3    29.2  869.28      39  864.72    77.9   843.6
    97.4     834   126.6  820.46   204.6  785.52   233.8  771.21   243.6  766.94
   253.3  763.45     263  761.09   282.5  757.78   292.3  755.54   321.5  745.98
   331.2   743.3     341  742.14   350.7   742.1   554.4  742.17   564.1  742.74
   573.8  743.84   583.5  745.23   593.2  747.26   622.2  756.07   670.7  769.37
   680.4  772.85   690.1  777.17   777.3  818.92   825.7  841.05   912.9  882.98
#Mann= 3 , 0 , 0
       0     .05       0     341    .035       0   554.4     .06       0
Bank Sta=341,554.4
XS Rating Curve= 0 ,0
Exp/Cntr=0.3,0.1

Type RM Length L Ch R = 1 ,528.8   ,313.2,298.6,284
XS GIS Cut Line= 4
     1856225.649      609072.076     1856017.316      608721.382
     1855925.302      608660.618     1855545.093      608514.785
#Sta/Elev= 30
       0  832.61    19.4  824.02    58.3  802.28    77.7  792.46   106.8  779.54
   145.7  763.86   155.4  761.35   165.1   760.6   194.2  761.28     204  763.11
   242.8  773.12   252.5  773.73   271.9  767.22   339.9  735.98   369.1  724.38
   388.5   718.7   398.2  717.07   444.7  713.54   453.8  713.24     463  713.77
   481.4  716.64     509  718.93   537.6  724.16     586  737.54   653.9   761.9
   721.8  781.71   741.2  789.39     780  806.76   857.5   843.9   925.4   872.8
#Mann= 3 , 0 , 0
       0     .05       0   444.7    .045       0     463     .06       0
Bank Sta=444.7,463
XS Rating Curve= 0 ,0
Exp/Cntr=0.3,0.1

Type RM Length L Ch R = 1 ,230.2   ,186.3,181,175.7
XS GIS Cut Line= 4
     1856685.718      608370.687     1856166.621      608430.149
     1856051.604       608436.66     1855590.232      608427.979
#Sta/Elev= 30
       0  867.14    67.7  834.94   280.6  748.93   290.3  746.76     300  746.36
     329  749.46   348.3  747.46     358  743.39   377.4  729.05     387  723.82
   416.1  720.05   445.1  713.54   454.8  712.77   503.1  718.21   560.9  714.07
   580.1  713.14   589.7  714.12   628.1  719.39   686.8  733.23   716.2  733.18
   735.9  735.46   824.2  758.72   912.6  771.96   951.9  781.62   971.5  787.94
   991.2   798.3  1020.6  823.38  1040.2   837.2  1050.1  842.37  1099.2  861.81
#Mann= 3 , 0 , 0
       0     .06       0   560.9    .045       0   589.7     .06       0
#XS Ineff= 2 , 0
          503.17  721.06
Permanent Ineff=
       F       F
Bank Sta=560.9,589.7
XS Rating Curve= 0 ,0
Exp/Cntr=0.3,0.1

Type RM Length L Ch R = 1 ,49.2    ,48.2,49.2,50.2
XS GIS Cut Line= 4
     1856466.968      608073.812     1856186.586      608227.458
     1856034.243      608274.333     1855591.534      608396.729
#Sta/Elev= 30
       0  854.24     126  804.95   232.5  759.49     310  725.07   319.7  721.86
   329.1  720.62   357.2  718.87   385.4  713.86   394.7  712.65   404.1  712.53
   415.1  713.84   432.2  716.97   498.7  719.25   537.8  722.73   557.3  725.35
   586.6  731.71   635.5  747.47     655  752.46   713.7  761.21   772.3  774.22
   791.8  779.14   811.4  785.54   821.2  789.74   830.9  795.26   840.7  802.67
     870  829.41   879.8  836.89   889.6  841.95   928.7  855.58   938.4  859.75
#Mann= 3 , 0 , 0
       0     .08       0   385.4    .045       0   415.1     .06       0
Bank Sta=385.4,415.1
XS Rating Curve= 0 ,0
Exp/Cntr=0.3,0.1

Chan Stop Cuts=-1
Use User Specified Reach Order=0
Composite Channel Slope=5